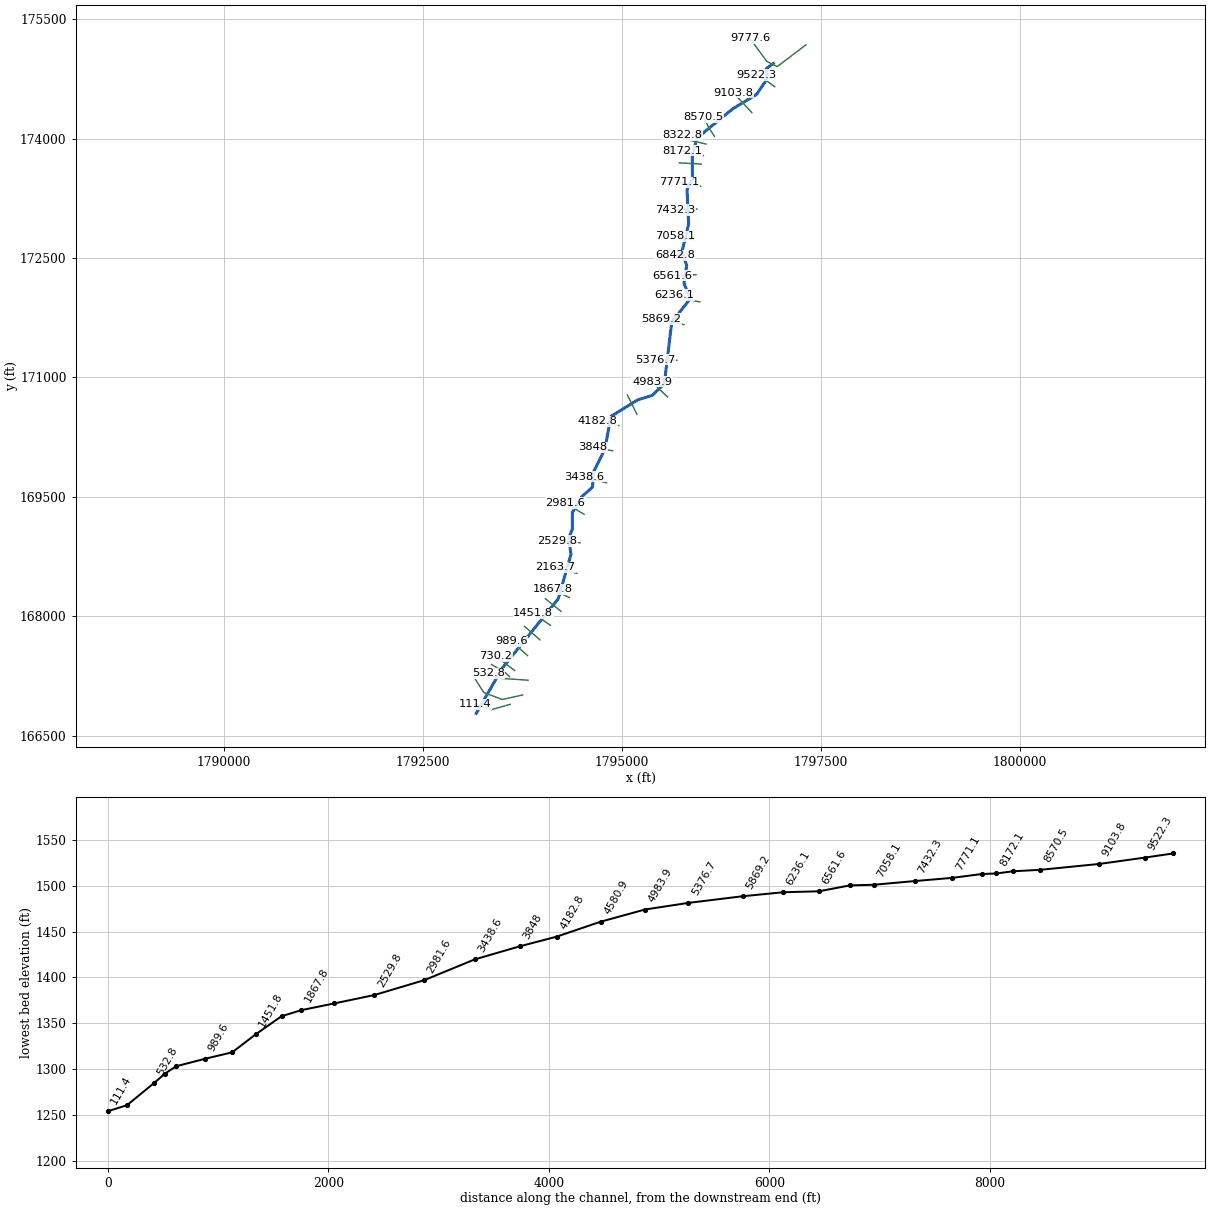
--- Shannon Branch.prj (project) ---

Proj Title=Shannon Branch
Current Plan=p01
Default Exp/Contr=0,0
English Units
Geom File=g01
Flow File=f01
Plan File=p01
BEGIN DESCRIPTION:
END DESCRIPTION:
DSS Export Rating Curves= 0
DSS Export Rating Curve Sorted= 0
DSS Export Volume Flow Curves= 0
DXF OffsetX= 0
DXF OffsetY= 0
DXF ScaleX= 0
DXF ScaleY= 0

--- Shannon Branch.p01 (plan) ---

Plan Title=Floodplain
Program Version=4.00
Geom File=g01
Flow File=f01
K Sum by GR=0
Std Step Tol=0.01
Critical Tol=0.01
Num of Std Step Trials=20
Max Error Tol=0.3
Flow Tol Ratio=0.001
Split Flow NTrial=30
Split Flow Tol=0.02
Split Flow Ratio=0.02
Log Output Level=0
Friction Slope Method=1
Unsteady Friction Slope Method=2
Unsteady Bridges Friction Slope Method=1
Global Log Level=0
CheckData=False
Run HTab=0
Run UNet=0
Run PostProcess=0
UNET Theta=0
UNET Theta Warmup=0
UNET ZTol=0
UNET ZSATol=0
UNET MxIter=0
UNET MaxInSteps=0
UNET DtIC=0
UNET DtMin=0
UNET MaxCRTS=0
UNET WFStab=0
UNET SFStab=0
UNET WFX=0
UNET SFX=0
UNET DSS MLevel=0
UNET DZMax Abort=0
UNET Convert EG Bridges=0
UNET Use Existing IB Tables=0
UNET Froude Limit=0
UNET Froude Power=0
Write IC File=0
Echo Input=False
Echo Output=False
Write Detailed=0

--- Shannon Branch.f01 (steady flow) ---

Flow Title=NFF Regression Equation
Program Version=4.00
Number of Profiles=1
Profile Names=P100yr
River Rch & RM=Shannon Branch,Main      ,9777.6
360.2704
River Rch & RM=Shannon Branch,Main      ,9522.3
703.4903
River Rch & RM=Shannon Branch,Main      ,8322.8
716.6096
River Rch & RM=Shannon Branch,Main      ,8039.2
818.6625
River Rch & RM=Shannon Branch,Main      ,6236.1
886.3207
River Rch & RM=Shannon Branch,Main      ,3848
978.3024
River Rch & RM=Shannon Branch,Main      ,286.2
1084.244
Boundary for River Rch & Prof#=Shannon Branch,Main      ,1
Up Type=0
Dn Type=3
Dn Slope=0.079971

--- Shannon Branch.g01 (geometry) ---

Geom Title=Geometry
Program Version=4.00

River Reach=Shannon Branch  ,Main
Reach XY= 30
      1796906.12      174943.375     1796816.634      174879.265
     1796826.696      174750.659     1796696.074        174556.5
     1796391.504      174371.227     1795948.011      174007.882
     1795886.733      173790.516     1795889.623      173492.794
     1795821.309      173359.281     1795841.062      172926.255
     1795754.925      172567.254      1795817.36      172409.433
     1795782.674      172184.551     1795860.718      171987.419
     1795629.478      171693.743     1795535.866      170920.054
     1795386.097      170775.719     1795200.675       170717.95
     1794863.588      170509.171     1794791.809        170105.7
     1794646.706       169813.18     1794633.987      169622.985
     1794496.356      169498.283     1794381.357      169303.295
     1794380.201       169091.71     1794336.266      168984.184
     1794363.436      168778.958      1794203.88      168219.934
     1793500.909      167348.736     1793173.808      166780.296

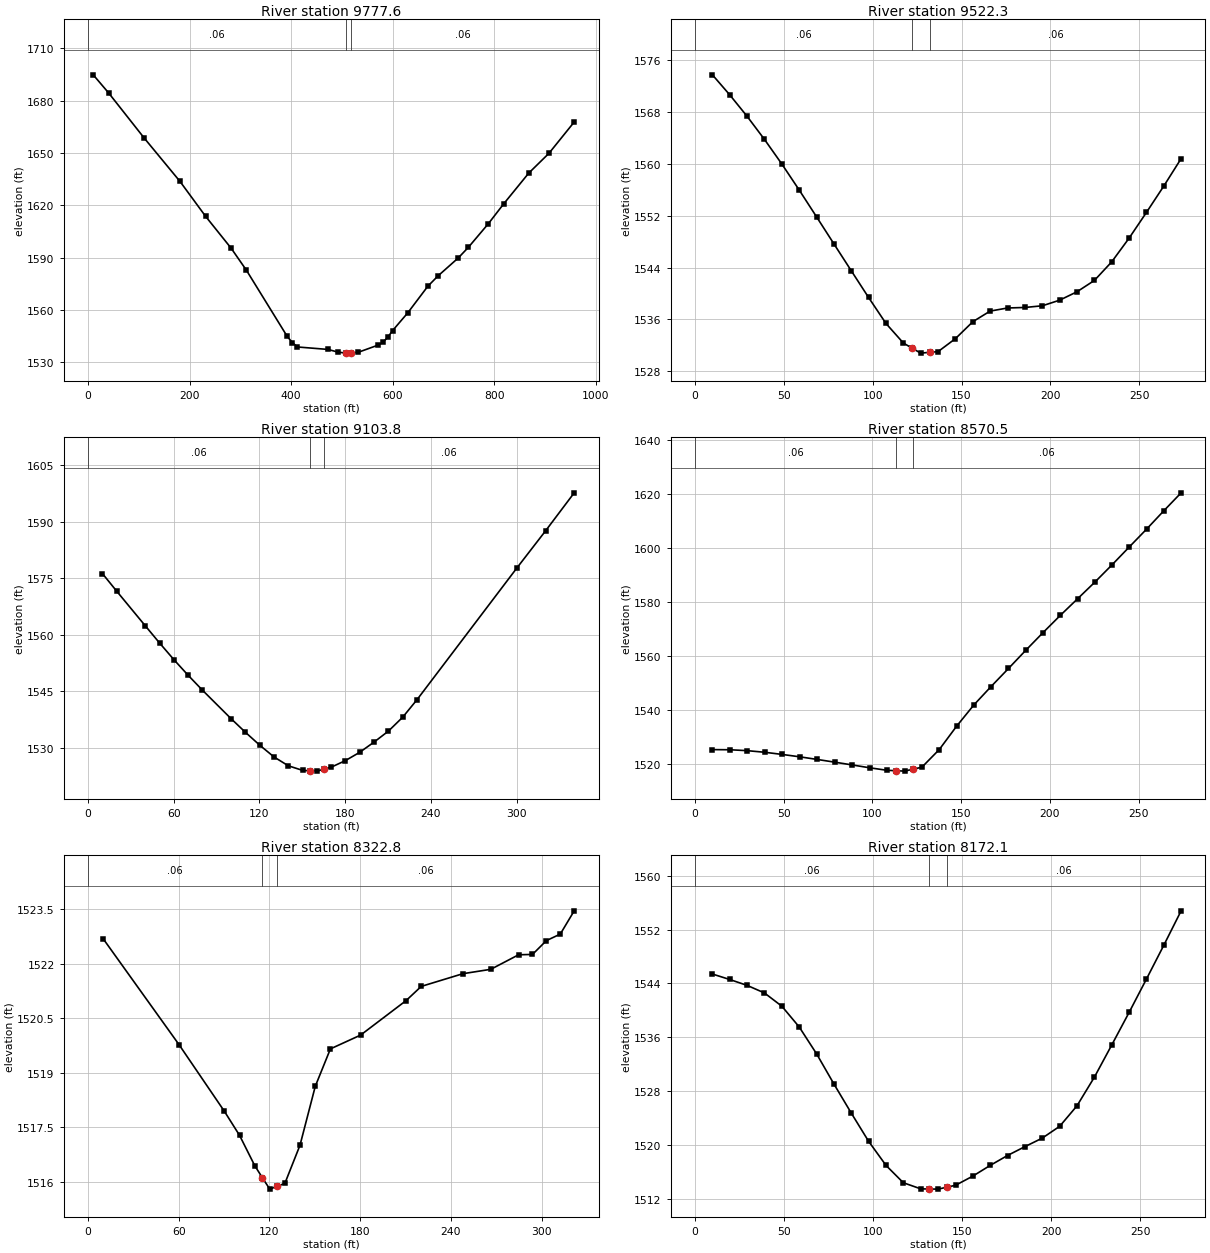
Type RM Length L Ch R = 1 ,9777.6  ,256.5,255.3,253
XS GIS Cut Line= 5
     1797314.566      175177.051     1796953.672      174904.062
     1796847.377      174957.835     1796822.863      174971.004
     1796610.944      175259.316
#Sta/Elev= 30
    10.1 1694.89    40.2 1684.59   110.6 1658.59     181 1633.75   231.3 1613.78
   281.6  1595.5   311.7 1582.87   392.2 1544.85   402.2 1541.36   412.3 1538.83
   472.4 1537.42   492.2 1535.87   507.1 1535.35   512.1  1535.3   517.1 1535.34
   531.9 1535.77   571.6 1539.95   580.9 1541.64   590.2 1544.39   599.5 1548.18
   629.3 1558.32     669 1573.63   688.9 1579.53   728.7 1589.81   748.6 1595.88
   788.3 1609.54   818.1 1620.78   867.8 1638.54   907.6 1649.89   957.3 1667.84
#Mann= 3 , 0 , 0
       0     .06       0   507.1    .045       0   517.1     .06       0
Bank Sta=507.1,517.1
XS Rating Curve= 0 ,0
Exp/Cntr=0.3,0.1

Type RM Length L Ch R = 1 ,9522.3  ,422.5,418.5,414.4
XS GIS Cut Line= 3
      1796923.65      174651.742     1796780.842      174754.448
     1796694.193      174799.656
#Sta/Elev= 30
     9.8 1573.71    19.5 1570.64    29.3 1567.32    39.1 1563.75    48.9 1559.95
    58.6 1555.97    68.4 1551.82    78.2 1547.64      88 1543.48    97.7 1539.38
   107.5 1535.37   117.3 1532.35     122  1531.6     127  1530.8     132 1530.92
   136.8 1531.03   146.6 1533.04   156.4 1535.65   166.1 1537.28   175.9 1537.76
   185.7 1537.84   195.5  1538.1   205.2 1538.96     215 1540.26   224.8 1542.01
   234.5 1544.86   244.3 1548.52   254.1  1552.5   263.9 1556.58   273.6 1560.79
#Mann= 3 , 0 , 0
       0     .06       0     122    .045       0     132     .06       0
Bank Sta=122,132
XS Rating Curve= 0 ,0
Exp/Cntr=0.3,0.1

Type RM Length L Ch R = 1 ,9103.8  ,536.9,533.4,529.6
XS GIS Cut Line= 2
     1796635.716      174325.961     1796404.475      174575.783
#Sta/Elev= 26
      10 1576.28      20  1571.6      40 1562.41    50.1  1557.8    60.1 1553.39
    70.1 1549.23    80.1 1545.28   100.1 1537.73   110.1 1534.13   120.1 1530.71
   130.2 1527.55   140.2 1525.21   150.2 1523.99   155.2 1523.89   160.2 1523.79
   165.2 1524.31   170.2 1524.83   180.2 1526.59   190.2 1528.79   200.2 1531.49
   210.3 1534.42   220.3 1538.11   230.3 1542.75   300.4 1577.82   320.4 1587.64
   340.4 1597.71
#Mann= 3 , 0 , 0
       0     .06       0   155.2    .045       0   165.2     .06       0
Bank Sta=155.2,165.2
XS Rating Curve= 0 ,0
Exp/Cntr=0.3,0.1

Type RM Length L Ch R = 1 ,8570.5  ,232.2,247.7,263.5
XS GIS Cut Line= 3
     1796164.958      174029.936     1796090.155      174145.599
     1796030.641      174268.198
#Sta/Elev= 30
     9.8 1525.36    19.7 1525.31    29.5 1524.97    39.4 1524.37    49.2 1523.57
      59  1522.7    68.9 1521.72    78.7 1520.72    88.5  1519.7    98.4 1518.64
   108.2 1517.71   113.1 1517.56   118.1  1517.4   123.1 1518.14   127.9 1518.86
   137.7  1525.4   147.5 1534.06   157.2  1541.9   166.9 1548.71   176.7 1555.38
   186.4 1562.08   196.2 1568.67   205.9 1575.02   215.6 1581.14   225.4 1587.34
   235.1 1593.75   244.8 1600.35   254.6 1606.98   264.3 1613.76     274 1620.37
#Mann= 3 , 0 , 0
       0     .06       0   113.1    .045       0   123.1     .06       0
Bank Sta=113.1,123.1
XS Rating Curve= 0 ,0
Exp/Cntr=0.3,0.1

Type RM Length L Ch R = 1 ,8322.8  ,150.6,150.7,150.5
XS GIS Cut Line= 3
     1796059.679      173931.613     1795844.955      173981.164
     1795766.499      174045.168
#Sta/Elev= 22
      10 1522.69    60.1 1519.78    90.2 1517.94   100.2 1517.28   110.2 1516.45
   115.2 1516.12   120.2  1515.8   125.2 1515.88   130.2 1515.96   140.2 1517.01
   150.3 1518.63   160.3 1519.66   180.3 1520.04   210.4 1520.99   220.4 1521.38
     248 1521.73   266.4 1521.85   284.8 1522.25     294 1522.26   303.2 1522.64
   312.4 1522.82   321.6 1523.46
#Mann= 3 , 0 , 0
       0     .06       0   115.2    .045       0   125.2     .06       0
Bank Sta=115.2,125.2
XS Rating Curve= 0 ,0
Exp/Cntr=0.3,0.1

Type RM Length L Ch R = 1 ,8172.1  ,129.4,132.8,136.5
XS GIS Cut Line= 3
     1796026.809      173786.506     1795893.697      173816.797
     1795761.027      173848.895
#Sta/Elev= 30
     9.8 1545.39    19.5 1544.58    29.3  1543.7      39 1542.58    48.8  1540.6
    58.5 1537.53    68.3 1533.52      78 1529.05    87.8  1524.7    97.5 1520.52
   107.3 1516.93     117 1514.36   126.8 1513.45   131.5 1513.43   136.5 1513.41
   141.5  1513.7   146.3 1513.98     156 1515.34   165.8 1516.94   175.5 1518.41
   185.3 1519.73     195 1520.99   204.8 1522.75   214.5 1525.79   224.3 1530.06
     234 1534.82   243.8 1539.69   253.5 1544.63   263.3 1549.68     273 1554.79
#Mann= 3 , 0 , 0
       0     .06       0   131.5    .045       0   141.5     .06       0
Bank Sta=131.5,141.5
XS Rating Curve= 0 ,0
Exp/Cntr=0.3,0.1

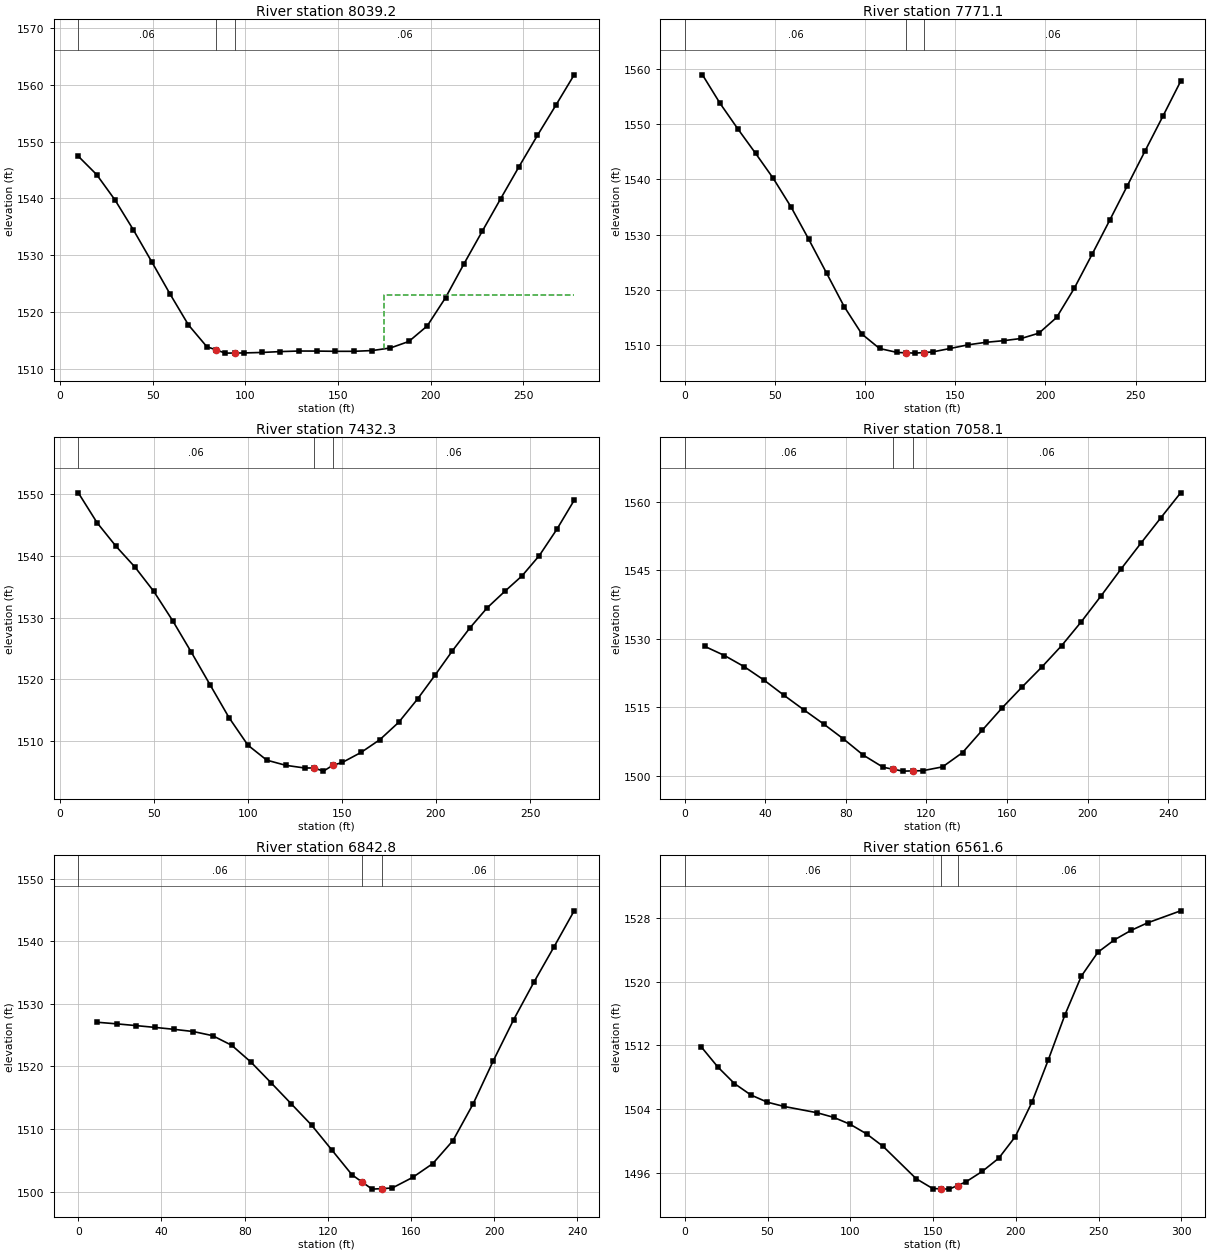
Type RM Length L Ch R = 1 ,8039.2  ,270.2,268.2,266.1
XS GIS Cut Line= 2
     1795999.506      173679.598      1795722.56      173694.984
#Sta/Elev= 30
     9.9 1547.41    19.8 1544.18    29.7 1539.72    39.6 1534.47    49.5 1528.86
    59.4 1523.18    69.3 1517.76    79.2 1513.94    84.2 1513.37    89.2  1512.8
    94.2 1512.82    99.1 1512.83     109 1512.92   118.9 1513.07   128.8 1513.17
   138.7 1513.16   148.6 1513.12   158.5 1513.12   168.4 1513.25   178.3 1513.71
   188.2 1514.85   198.1 1517.57     208 1522.54   217.9 1528.47   227.8 1534.22
   237.7 1539.92   247.7 1545.61   257.6 1551.09   267.5 1556.37   277.4 1561.73
#Mann= 3 , 0 , 0
     9.9     .06       0    84.2    .045       0    94.2     .06       0
#XS Ineff= 2 , 0
                          174.66         1523.06
Permanent Ineff=
       F       F
Bank Sta=84.2,94.2
XS Rating Curve= 0 ,0
Exp/Cntr=0.3,0.1

Type RM Length L Ch R = 1 ,7771.1  ,334.5,338.8,342.8
XS GIS Cut Line= 2
      1795993.61      173400.998     1795723.141      173450.549
#Sta/Elev= 30
     9.8 1558.91    19.6 1553.73    29.5  1549.1    39.3  1544.7    49.1 1540.18
    58.9 1535.04    68.7 1529.21    78.6 1523.09    88.4 1517.02    98.2 1512.06
     108 1509.45   117.8 1508.73   122.7 1508.67   127.7 1508.61   132.7 1508.72
   137.5 1508.83   147.3 1509.46   157.1 1510.11   166.9 1510.56   176.8 1510.86
   186.6 1511.26   196.4 1512.22   206.2 1515.05     216 1520.32   225.9 1526.47
   235.7 1532.65   245.5  1538.9   255.3 1545.17   265.2 1551.45     275 1557.74
#Mann= 3 , 0 , 0
       0     .06       0   122.7    .045       0   132.7     .06       0
Bank Sta=122.7,132.7
XS Rating Curve= 0 ,0
Exp/Cntr=0.3,0.1

Type RM Length L Ch R = 1 ,7432.3  ,378.3,374.2,370.1
XS GIS Cut Line= 3
     1795946.412      173115.524     1795756.175      173114.012
     1795673.659       173103.56
#Sta/Elev= 30
      10 1550.21      20 1545.35      30 1541.56    40.1 1538.18    50.1 1534.24
    60.1 1529.51    70.1 1524.36    80.1 1519.06    90.1 1513.78   100.1 1509.34
   110.1 1506.92   120.2 1506.08   130.2 1505.65   135.2 1505.65  140.22 1505.14
   145.2 1506.09   150.2 1506.54   160.2 1508.17   170.2 1510.24   180.2 1513.05
   190.2 1516.82   199.5 1520.68   208.7 1524.62     218 1528.33   227.2 1531.59
   236.5 1534.24   245.7 1536.76   254.9 1540.05   264.2  1544.3   273.4    1549
#Mann= 3 , 0 , 0
      10     .06       0   135.2    .045       0   145.2     .06       0
Bank Sta=135.2,145.2
XS Rating Curve= 0 ,0
Exp/Cntr=0.3,0.1

Type RM Length L Ch R = 1 ,7058.1  ,209.5,215.3,221.1
XS GIS Cut Line= 2
     1795906.895      172727.922     1795665.331      172775.409
#Sta/Elev= 27
     9.8 1528.38    19.7 1526.36    29.5 1523.92    39.4 1520.96    49.2 1517.68
    59.1 1514.49    68.9  1511.4    78.8 1508.11    88.6 1504.59    98.5 1501.92
   103.3 1501.51   108.3 1501.08   113.3 1501.13   118.2 1501.18     128 1502.01
   137.9 1505.13   147.7 1510.03   157.6 1514.93   167.4 1519.44   177.3 1523.85
   187.1 1528.51   196.9 1533.75   206.8 1539.46   216.6 1545.27   226.5 1550.93
   236.3 1556.43   246.2 1561.93
#Mann= 3 , 0 , 0
       0     .06       0   103.3    .045       0   113.3     .06       0
Bank Sta=103.3,113.3
XS Rating Curve= 0 ,0
Exp/Cntr=0.3,0.1

Type RM Length L Ch R = 1 ,6842.8  ,283.1,281.2,279.3
XS GIS Cut Line= 3
      1795904.83      172554.492     1795822.244      172546.233
     1795667.395      172531.781
#Sta/Elev= 27
     9.2 1527.05    18.4  1526.8    27.7 1526.52    36.9 1526.23    46.1 1525.92
    55.3 1525.57    64.6 1524.91    73.8 1523.37      83  1520.7    92.7 1517.39
   102.4 1514.03   112.2 1510.62   121.9 1506.67   131.6  1502.7   136.3 1501.58
   141.3  1500.4   146.3 1500.49     151 1500.58   160.8 1502.27   170.5 1504.48
   180.2 1508.15   189.9 1514.01   199.6  1520.9   209.4 1527.47   219.1 1533.43
   228.8 1539.09   238.5 1544.85
#Mann= 3 , 0 , 0
       0     .06       0   136.3    .045       0   146.3     .06       0
Bank Sta=136.3,146.3
XS Rating Curve= 0 ,0
Exp/Cntr=0.3,0.1

Type RM Length L Ch R = 1 ,6561.6  ,334.7,325.6,316.2
XS GIS Cut Line= 2
       1795935.8      172290.217     1795636.426      172279.894
#Sta/Elev= 29
      10 1511.79      20 1509.27      30  1507.2    39.9 1505.77    49.9 1504.86
    59.9 1504.33    79.9 1503.54    89.9 1502.96    99.9 1502.09   109.8 1500.89
   119.8 1499.32   139.8 1495.26   149.8 1494.02   154.8 1493.99   159.8 1493.95
   164.8  1494.4   169.7 1494.84   179.7 1496.17   189.7 1497.83   199.7 1500.54
   209.7 1504.83   219.7 1510.21   229.7 1515.83   239.6 1520.68   249.6 1523.68
   259.6 1525.24   269.6 1526.42   279.6 1527.37   299.6 1528.88
#Mann= 3 , 0 , 0
       0     .06       0   154.8    .045       0   164.8     .06       0
Bank Sta=154.8,164.8
XS Rating Curve= 0 ,0
Exp/Cntr=0.3,0.1

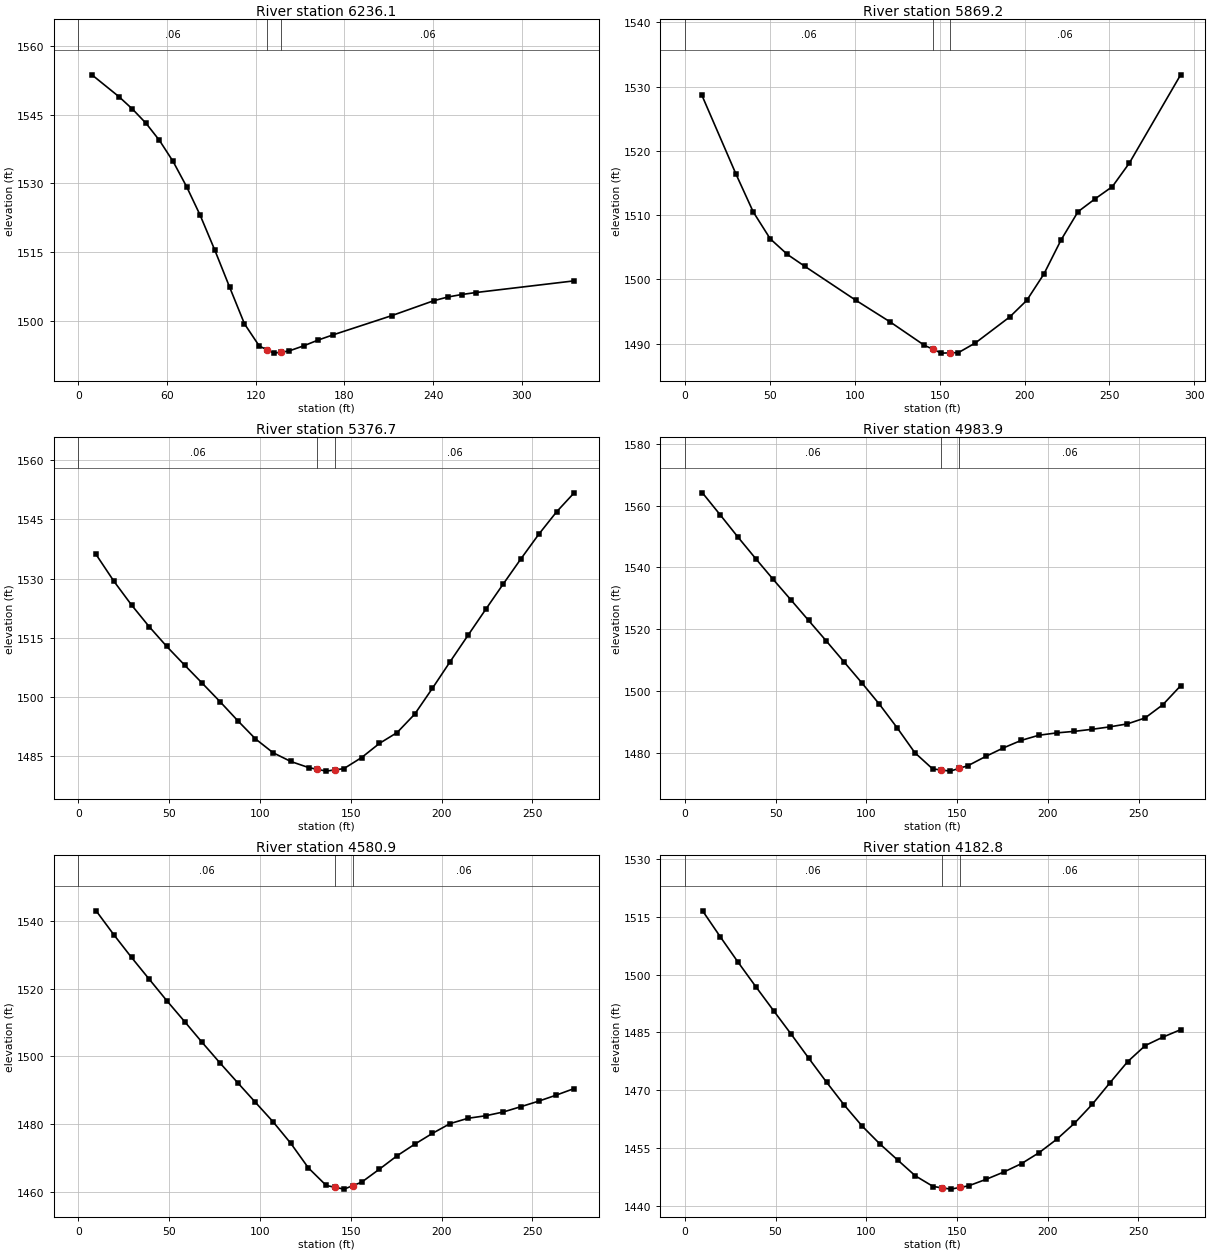
Type RM Length L Ch R = 1 ,6236.1  ,363.6,366.9,370.4
XS GIS Cut Line= 4
     1795983.287       171949.55     1795902.072      171963.495
     1795791.803      172010.754     1795661.201      172036.265
#Sta/Elev= 25
     9.2 1553.72    27.5 1548.94    36.6 1546.24    45.8 1543.13    54.9 1539.38
    64.1 1534.79    73.2 1529.31    82.4 1523.05    92.4 1515.35   102.4 1507.27
   112.4  1499.3   122.4 1494.46   127.4 1493.68   132.4 1492.91   137.4 1493.14
   142.4 1493.37   152.4  1494.5   162.4 1495.79   172.4 1496.91   211.9 1501.09
   240.4 1504.36   249.9 1505.17   259.4 1505.72   268.9 1506.15   335.4  1508.7
#Mann= 3 , 0 , 0
       0     .06       0   127.4    .045       0   137.4     .06       0
Bank Sta=127.4,137.4
XS Rating Curve= 0 ,0
Exp/Cntr=0.3,0.1

Type RM Length L Ch R = 1 ,5869.2  ,487.8,492.5,497.3
XS GIS Cut Line= 2
     1795783.016      171662.564     1795500.159      171734.826
#Sta/Elev= 23
    10.1 1528.63    30.2 1516.35    40.3  1510.5    50.3 1506.32    60.4 1503.89
    70.5 1502.07   100.7 1496.76   120.8 1493.41   140.9 1489.78     146 1489.15
     151 1488.54     156 1488.58   161.1 1488.62   171.1 1490.13   191.3 1494.17
   201.3 1496.74   211.4 1500.84   221.5 1506.14   231.5 1510.54   241.6 1512.55
   251.7 1514.44   261.7  1518.1   291.9 1531.83
#Mann= 3 , 0 , 0
       0     .06       0     146    .045       0     156     .06       0
Bank Sta=146,156
XS Rating Curve= 0 ,0
Exp/Cntr=0.3,0.1

Type RM Length L Ch R = 1 ,5376.7  ,407.7,392.8,377.3
XS GIS Cut Line= 3
     1795693.594      171215.563     1795557.114      171217.916
     1795420.635      171220.269
#Sta/Elev= 30
     9.7 1536.13    19.5 1529.37    29.3  1523.3      39 1517.83    48.7 1512.81
    58.5 1508.11    68.2 1503.53      78 1498.86    87.8 1494.03    97.5 1489.45
   107.2 1485.94     117 1483.72   126.8 1482.18   131.5 1481.75   136.5 1481.28
   141.5 1481.61   146.2 1481.91     156 1484.72   165.8  1488.3   175.5 1491.03
   185.2 1495.69     195 1502.26   204.7 1508.96   214.5  1515.6   224.3  1522.2
     234 1528.65   243.7 1534.99   253.5 1541.19   263.3 1546.86     273 1551.68
#Mann= 3 , 0 , 0
       0     .06       0   131.5    .045       0   141.5     .06       0
Bank Sta=131.5,141.5
XS Rating Curve= 0 ,0
Exp/Cntr=0.3,0.1

Type RM Length L Ch R = 1 ,4983.9  ,410.1,403,396.4
XS GIS Cut Line= 3
     1795577.273       170754.98     1795477.955      170848.601
     1795381.265      170945.045
#Sta/Elev= 30
     9.7 1564.14    19.5 1557.01    29.2 1549.87      39 1542.88    48.7 1536.11
    58.5 1529.46    68.2 1522.83      78 1516.15    87.7 1509.42    97.5 1502.64
   107.2 1495.71     117 1488.06   126.7 1480.04   136.5 1474.79   141.2 1474.44
   146.2 1474.07   151.2 1474.98     156 1475.84   165.8 1478.84   175.5 1481.59
   185.3 1484.02     195 1485.68   204.8 1486.44   214.5 1486.94   224.3 1487.61
     234 1488.39   243.8 1489.36   253.5 1491.27   263.3 1495.56   273.1  1501.7
#Mann= 3 , 0 , 0
       0     .06       0   141.2    .045       0   151.2     .06       0
Bank Sta=141.2,151.2
XS Rating Curve= 0 ,0
Exp/Cntr=0.3,0.1

Type RM Length L Ch R = 1 ,4580.9  ,379.9,398.1,417.5
XS GIS Cut Line= 3
     1795192.154      170537.044     1795131.521      170659.338
     1795070.888      170781.632
#Sta/Elev= 30
     9.8 1543.08    19.5 1536.04    29.3 1529.28      39 1522.87    48.7  1516.5
    58.5 1510.32    68.2 1504.13      78 1498.06    87.8 1492.18    97.5 1486.41
   107.2 1480.67     117 1474.26   126.7 1466.99   136.5 1461.81   141.2 1461.29
   146.3 1460.73   151.2 1461.77     156 1462.79   165.8 1466.65   175.5  1470.6
   185.2 1474.02     195 1477.24   204.7 1480.12   214.5 1481.69   224.3 1482.44
     234 1483.56   243.7 1485.13   253.5 1486.77   263.2 1488.56     273 1490.49
#Mann= 3 , 0 , 0
       0     .06       0   141.2    .045       0   151.2     .06       0
Bank Sta=141.2,151.2
XS Rating Curve= 0 ,0
Exp/Cntr=0.3,0.1

Type RM Length L Ch R = 1 ,4182.8  ,333.7,334.8,334.8
XS GIS Cut Line= 3
     1794965.243      170394.632     1794832.006      170425.951
     1794697.407      170448.256
#Sta/Elev= 30
     9.8  1516.5    19.6 1509.75    29.3 1503.24    39.1 1496.89    48.9 1490.68
    58.7 1484.52    68.4 1478.29    78.2  1472.1      88 1466.15    97.8 1460.75
   107.5 1456.16   117.3    1452   127.1 1447.88   136.9 1445.13   141.6  1444.8
   146.6 1444.45   151.6 1444.88   156.4  1445.3   166.1 1446.99   175.9 1448.89
   185.6 1451.06   195.3 1453.89   205.1 1457.39   214.8 1461.51   224.6 1466.41
   234.3 1471.96   244.1 1477.45   253.8 1481.62   263.6 1483.82   273.3 1485.73
#Mann= 3 , 0 , 0
       0     .06       0   141.6    .045       0   151.6     .06       0
Bank Sta=141.6,151.6
XS Rating Curve= 0 ,0
Exp/Cntr=0.3,0.1

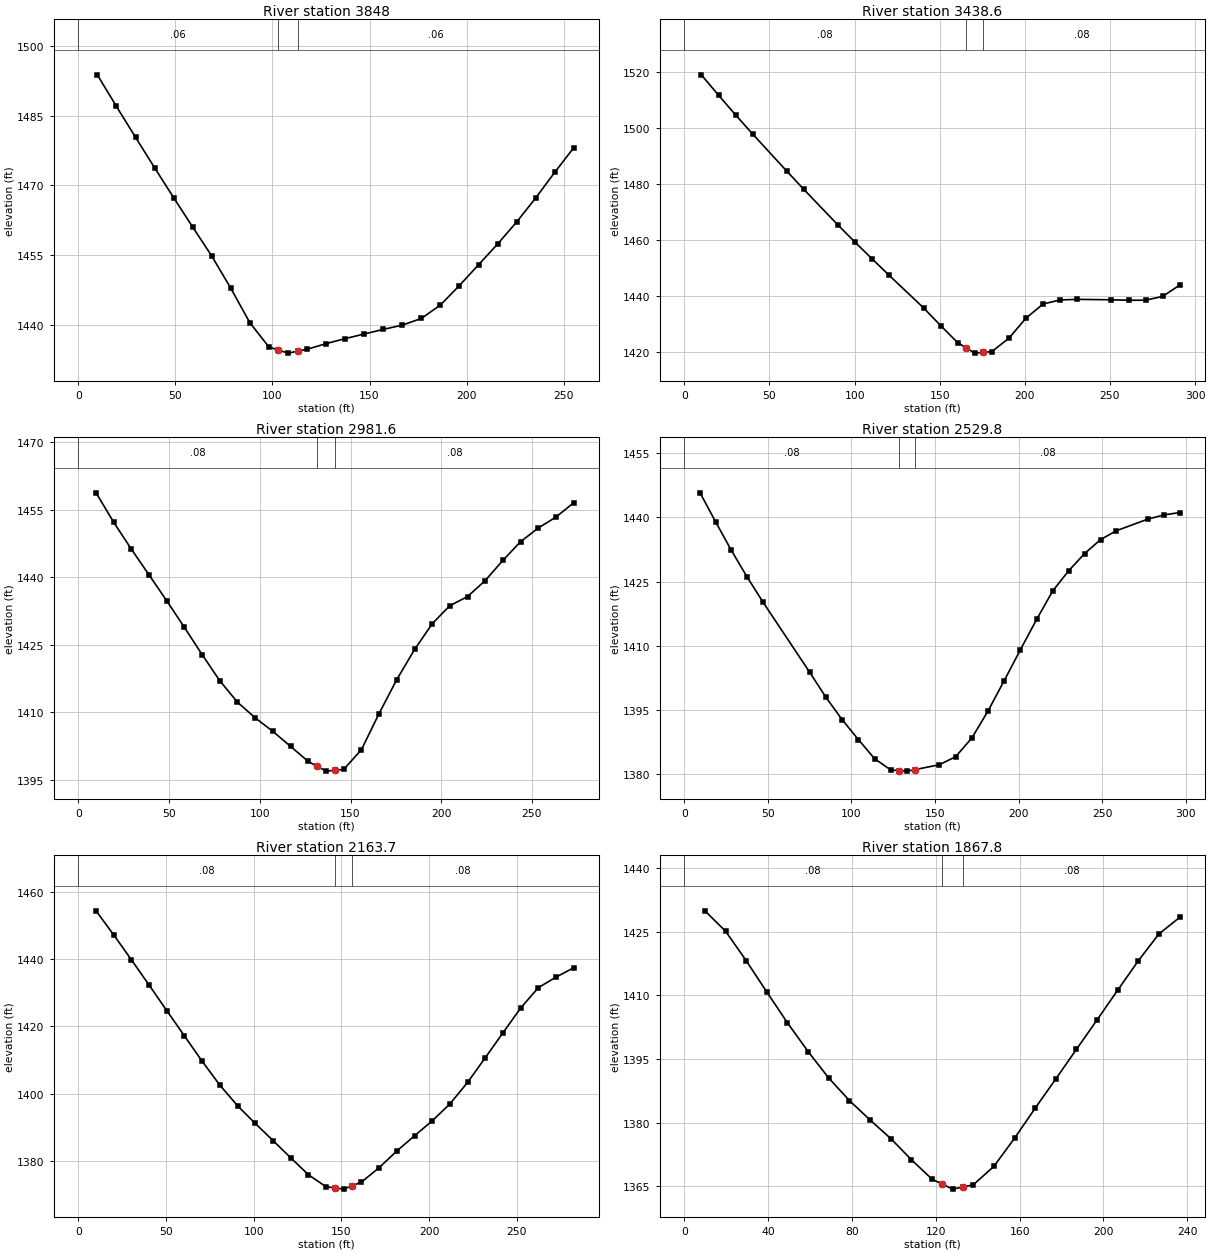
Type RM Length L Ch R = 1 ,3848    ,411.7,409.3,407
XS GIS Cut Line= 2
     1794889.023      170078.978     1794637.136      170120.271
#Sta/Elev= 28
     9.8 1493.82    19.6 1487.04    29.5 1480.36    39.3 1473.81    49.1 1467.37
    58.9 1461.06    68.7 1454.83    78.5  1447.9    88.4 1440.42    98.2 1435.22
     103 1434.57     108  1433.9     113 1434.32   117.8 1434.72   127.6 1435.94
   137.4 1437.02   147.3 1438.02   157.1 1439.01   166.9 1439.93   176.7 1441.36
   186.5 1444.25   196.3 1448.45   206.2 1452.94     216  1457.4   225.8 1462.14
   235.6 1467.31   245.4 1472.82   255.2 1478.12
#Mann= 3 , 0 , 0
       0     .06       0     103    .045       0     113     .06       0
Bank Sta=103,113
XS Rating Curve= 0 ,0
Exp/Cntr=0.3,0.1

Type RM Length L Ch R = 1 ,3438.6  ,462.2,457,451.8
XS GIS Cut Line= 2
     1794810.566      169676.371     1794529.774      169752.763
#Sta/Elev= 27
      10 1518.92    20.1 1511.63    30.1 1504.62    40.1  1497.8    60.2 1484.53
    70.2 1478.02    90.3 1465.28   100.3 1459.16   110.4 1453.17   120.4 1447.31
   140.5 1435.75   150.5 1429.44   160.6 1423.31   165.6 1421.45   170.6 1419.59
   175.6 1419.85   180.6 1420.12   190.7 1424.95   200.7 1432.08   210.7 1437.12
   220.8 1438.58   230.8 1438.78   250.9 1438.63   260.9 1438.46   270.9 1438.48
     281 1439.84     291 1443.89
#Mann= 3 , 0 , 0
       0     .08       0   165.6    .045       0   175.6     .08       0
Bank Sta=165.6,175.6
XS Rating Curve= 0 ,0
Exp/Cntr=0.3,0.1

Type RM Length L Ch R = 1 ,2981.6  ,438.8,451.8,464.9
XS GIS Cut Line= 3
     1794528.598      169280.194     1794411.969      169351.117
     1794295.341       169422.04
#Sta/Elev= 30
     9.8 1458.81    19.5 1452.27    29.3 1446.25      39 1440.56    48.7 1434.84
    58.5 1428.89    68.3 1422.82      78 1417.03    87.7 1412.29    97.5  1408.8
   107.2  1405.8     117 1402.46   126.7 1399.11   131.5 1398.06   136.5 1396.97
   141.5 1397.16   146.2 1397.34     156 1401.73   165.7 1409.74   175.5 1417.33
   185.3    1424     195 1429.71   204.7 1433.73   214.5 1435.76   224.2 1439.31
     234 1443.82   243.7 1447.95   253.5 1451.01   263.2 1453.42     273 1456.61
#Mann= 3 , 0 , 0
       0     .08       0   131.5    .045       0   141.5     .08       0
Bank Sta=131.5,141.5
XS Rating Curve= 0 ,0
Exp/Cntr=0.3,0.1

Type RM Length L Ch R = 1 ,2529.8  ,373.8,366.1,358.3
XS GIS Cut Line= 4
     1794478.158      168922.774      1794403.83      168933.098
     1794259.305       168916.58     1794189.107      168945.486
#Sta/Elev= 29
     9.4 1445.73    18.8  1438.9    28.1 1432.32    37.5 1426.13    46.9 1420.32
      75 1403.85    84.7 1398.01    94.4  1392.8   104.1 1388.16   113.8 1383.69
   123.5 1381.06   128.2 1380.92   133.2 1380.78   138.2 1381.15   152.6 1382.27
   162.3 1384.15     172  1388.5   181.7 1394.83   191.4 1401.92   201.1 1409.14
   210.8 1416.21   220.5 1422.89     230 1427.57   239.5 1431.56     249 1434.81
   258.5 1436.89   277.4 1439.61   286.9 1440.57   296.4 1441.13
#Mann= 3 , 0 , 0
       0     .08       0   128.2    .045       0   138.2     .08       0
Bank Sta=128.2,138.2
XS Rating Curve= 0 ,0
Exp/Cntr=0.3,0.1

Type RM Length L Ch R = 1 ,2163.7  ,299.6,295.9,292
XS GIS Cut Line= 2
     1794436.865       168538.75     1794164.331      168613.077
#Sta/Elev= 30
    10.1 1454.33    20.2 1447.17    30.3 1439.75    40.4 1432.23    50.4 1424.68
    60.5 1417.14    70.6 1409.61    80.7 1402.49    90.8 1396.36   100.9 1391.09
     111 1386.02   121.1 1380.89   131.2 1375.85   141.2 1372.29   146.3 1371.92
   151.3 1371.56   156.3 1372.59   161.4 1373.63   171.5 1377.93   181.6 1382.89
   191.7 1387.42   201.8 1391.87   211.9 1396.91     222 1403.32     232  1410.6
   242.1 1418.02   252.2  1425.4   262.3 1431.47   272.4 1434.62   282.5 1437.39
#Mann= 3 , 0 , 0
       0     .08       0   146.3    .045       0   156.3     .08       0
Bank Sta=146.3,156.3
XS Rating Curve= 0 ,0
Exp/Cntr=0.3,0.1

Type RM Length L Ch R = 1 ,1867.8  ,185,180.3,175.7
XS GIS Cut Line= 2
     1794343.955      168235.246     1794131.297      168338.479
#Sta/Elev= 26
     9.8 1429.94    19.7 1425.12    29.5  1418.2    39.4 1410.75    49.2 1403.53
    59.1 1396.72    68.9  1390.5    78.8 1385.17    88.6 1380.61    98.5 1376.22
   108.3 1371.25   118.2 1366.63     123 1365.49     128 1364.29     133 1364.81
   137.9 1365.32   147.7 1369.66   157.6 1376.32   167.4 1383.38   177.3 1390.32
   187.1 1397.27     197 1404.25   206.8 1411.24   216.7 1418.21   226.5 1424.51
   236.4  1428.4
#Mann= 3 , 0 , 0
       0     .08       0     123    .045       0     133     .08       0
Bank Sta=123,133
XS Rating Curve= 0 ,0
Exp/Cntr=0.3,0.1

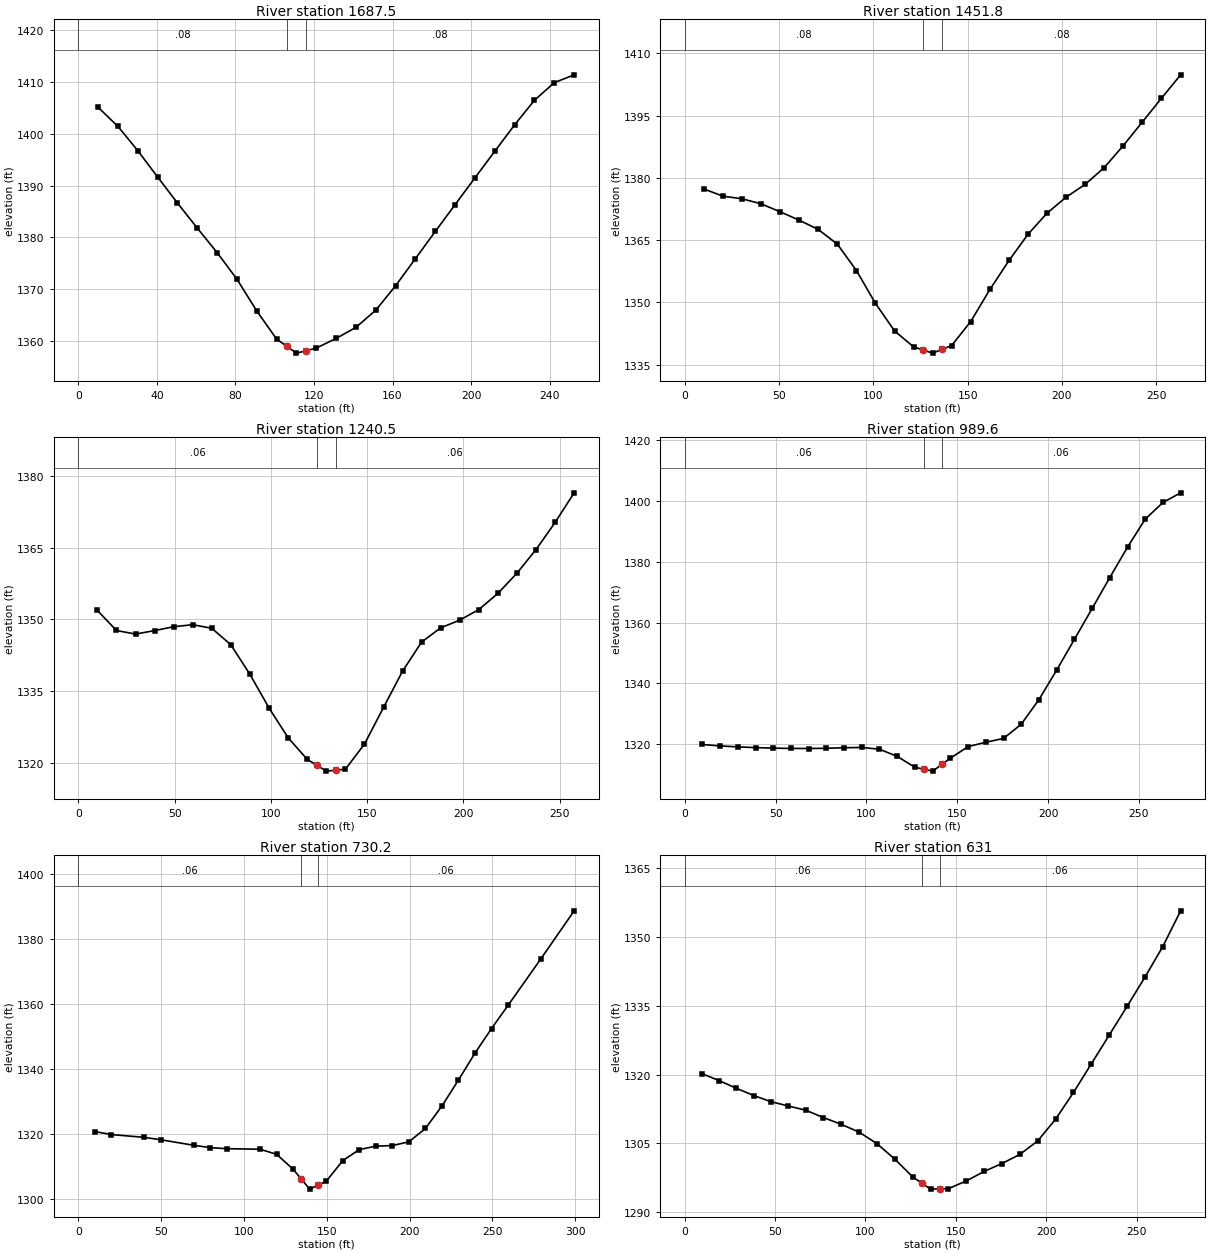
Type RM Length L Ch R = 1 ,1687.5  ,234.2,235.8,237.4
XS GIS Cut Line= 2
     1794238.658      168061.816     1794042.517      168220.794
#Sta/Elev= 27
    10.1  1405.1    20.2 1401.41    30.3 1396.73    40.4 1391.64    50.5 1386.63
    60.6 1381.78    70.7 1377.06    80.8 1371.91    90.9 1365.78     101 1360.36
   106.1 1358.99   111.1 1357.66   116.1 1358.14   121.2 1358.64   131.3  1360.5
   141.4 1362.64   151.5 1365.96   161.6 1370.68   171.7 1375.92   181.8 1381.15
   191.9 1386.34     202 1391.51   212.1 1396.63   222.2 1401.74   232.3 1406.48
   242.4 1409.87   252.5 1411.38
#Mann= 3 , 0 , 0
       0     .08       0   106.1    .045       0   116.1     .08       0
Bank Sta=106.1,116.1
XS Rating Curve= 0 ,0
Exp/Cntr=0.3,0.1

Type RM Length L Ch R = 1 ,1451.8  ,213.7,211.3,208.8
XS GIS Cut Line= 2
     1794106.521      167886.321     1793889.733      168034.975
#Sta/Elev= 28
    10.1 1377.32    20.2 1375.58    30.3 1374.95    40.4 1373.75    50.5 1371.83
    60.7 1369.78    70.8 1367.55    80.9    1364      91 1357.67   101.1 1349.74
   111.2 1343.12   121.3 1339.27   126.4 1338.51   131.4 1337.76   136.4 1338.66
   141.5 1339.59   151.6 1345.38   161.8 1353.11   171.9 1360.08     182 1366.42
   192.1  1371.5   202.2 1375.35   212.3 1378.43   222.4 1382.47   232.5 1387.76
   242.6 1393.45   252.7 1399.15   262.9 1404.82
#Mann= 3 , 0 , 0
       0     .08       0   126.4    .045       0   136.4     .08       0
Bank Sta=126.4,136.4
XS Rating Curve= 0 ,0
Exp/Cntr=0.3,0.1

Type RM Length L Ch R = 1 ,1240.5  ,251,250.9,250.9
XS GIS Cut Line= 2
     1793973.679      167703.951     1793779.602      167873.252
#Sta/Elev= 28
     9.9 1351.86    19.8 1347.67    29.7 1346.92    39.6 1347.65    49.5 1348.46
    59.4 1348.88    69.3 1348.14    79.2 1344.69    89.1 1338.51    99.1 1331.43
     109 1325.22   118.9 1320.72   123.8 1319.51   128.8 1318.27   133.8 1318.47
   138.7 1318.67   148.6 1323.92   158.5 1331.59   168.4 1339.18   178.3 1345.27
   188.2 1348.23   198.1 1349.84     208 1352.05   217.9 1355.42   227.8 1359.66
   237.7 1364.59   247.6 1370.26   257.5 1376.45
#Mann= 3 , 0 , 0
       0     .06       0   123.8    .045       0   133.8     .06       0
Bank Sta=123.8,133.8
XS Rating Curve= 0 ,0
Exp/Cntr=0.3,0.1

Type RM Length L Ch R = 1 ,989.6   ,257.8,259.4,261
XS GIS Cut Line= 3
     1793817.969      167506.342     1793715.852      167596.917
     1793613.464      167687.198
#Sta/Elev= 30
     9.7 1319.84    19.5 1319.36    29.2 1319.06      39 1318.81    48.7 1318.64
    58.5 1318.54    68.2 1318.52      78 1318.59    87.7 1318.77    97.5 1318.86
   107.2 1318.29     117 1315.91   126.7 1312.33   131.5 1311.71   136.5 1311.07
   141.5 1313.26   146.2 1315.32     156 1319.15   165.7 1320.57   175.5 1321.84
   185.2 1326.48     195 1334.62   204.8 1344.39   214.5 1354.45   224.3 1364.64
     234 1374.81   243.8 1384.87   253.5 1394.03   263.3 1399.55     273 1402.71
#Mann= 3 , 0 , 0
       0     .06       0   131.5    .045       0   141.5     .06       0
Bank Sta=131.5,141.5
XS Rating Curve= 0 ,0
Exp/Cntr=0.3,0.1

Type RM Length L Ch R = 1 ,730.2   ,97,99.1,101.2
XS GIS Cut Line= 2
     1793656.427      167318.542     1793416.928      167498.167
#Sta/Elev= 27
      10 1320.71      20  1319.8    39.9 1318.93    49.9 1318.19    69.9 1316.48
    79.8 1315.76    89.8 1315.45   109.8 1315.27   119.7 1313.72   129.7 1309.12
   134.7 1306.06   139.7 1302.99   144.7 1304.21   149.7 1305.42   159.7 1311.78
   169.6 1315.16   179.6 1316.21   189.6 1316.41   199.6 1317.56   209.6 1321.69
   219.5 1328.55   229.5 1336.57   239.5 1344.87   249.5 1352.46   259.5  1359.6
   279.4    1374   299.4 1388.71
#Mann= 3 , 0 , 0
       0     .06       0   134.7    .045       0   144.7     .06       0
Bank Sta=134.7,144.7
XS Rating Curve= 0 ,0
Exp/Cntr=0.3,0.1

Type RM Length L Ch R = 1 ,631     ,94,98.3,102.5
XS GIS Cut Line= 3
     1793592.582      167240.786     1793544.936      167287.572
     1793366.798      167394.247
#Sta/Elev= 30
     9.5 1320.18    19.1 1318.66    28.6 1316.99    38.2 1315.42    47.7 1314.09
    57.2 1313.16    66.8 1312.25    76.7 1310.64    86.6 1309.16    96.4 1307.48
   106.3 1304.98   116.2  1301.6   126.1 1297.74     131 1296.42     136 1295.07
     141 1295.12   145.9 1295.17   155.8 1296.86   165.7 1298.92   175.5 1300.64
   185.4 1302.61   195.3 1305.56   205.2 1310.28   215.1 1316.09     225 1322.33
   234.9 1328.58   244.8 1334.84   254.6 1341.14   264.5  1347.8   274.4  1355.6
#Mann= 3 , 0 , 0
       0     .06       0     131    .045       0     141     .06       0
Bank Sta=131,141
XS Rating Curve= 0 ,0
Exp/Cntr=0.3,0.1

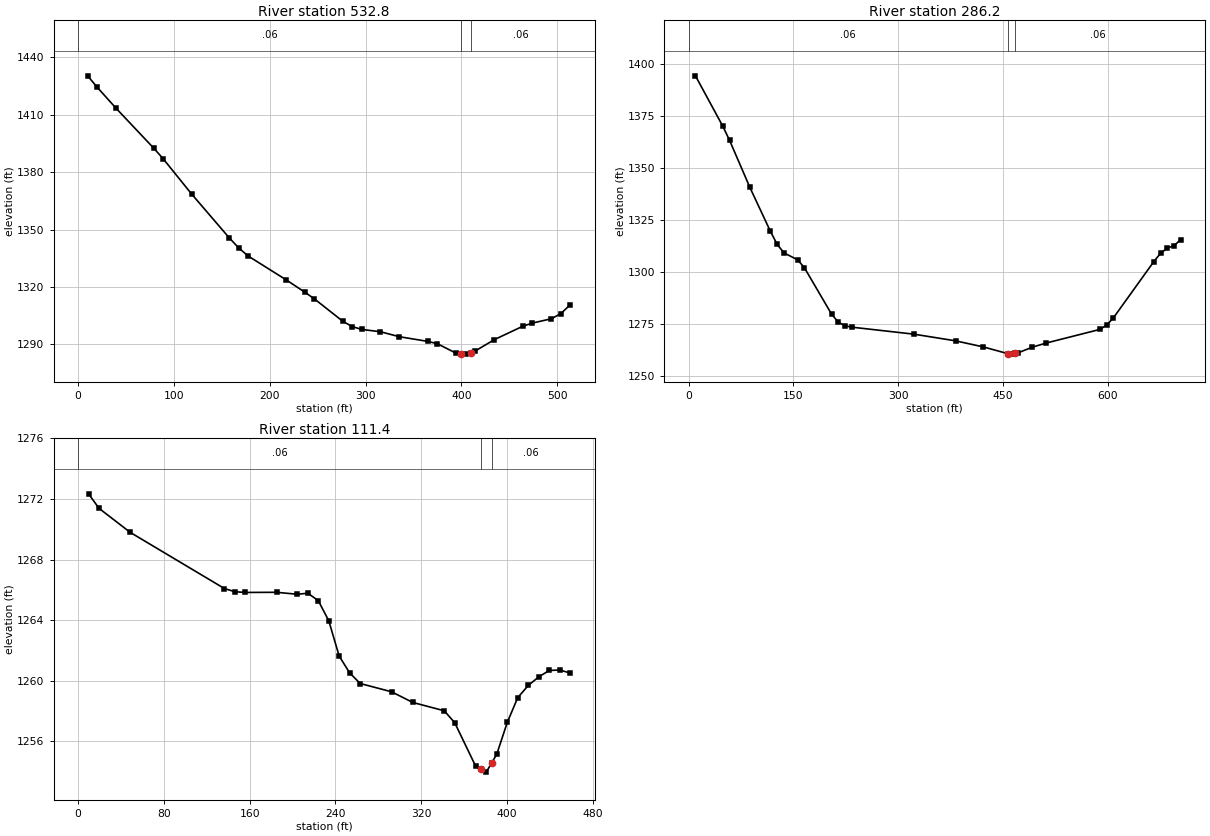
Type RM Length L Ch R = 1 ,532.8   ,247.4,246.6,245.9
XS GIS Cut Line= 3
     1793825.729      167196.728     1793491.255      167219.439
     1793324.019      167281.379
#Sta/Elev= 30
     9.9 1430.32    19.7 1424.45    39.4 1413.46    78.9 1392.51    88.7 1387.01
   118.3 1368.63   157.8  1345.6   167.6 1340.37   177.5 1336.15   216.9 1323.78
   236.6 1317.26   246.5 1313.79   276.1 1302.11   285.9 1299.33   295.8 1297.83
   315.5  1296.6   335.2 1294.01     365 1291.55   374.9 1290.35   394.7 1285.32
   399.6 1285.12   404.6 1284.91   409.6 1285.76   414.5  1286.6   434.3 1292.47
     464 1299.47     474 1301.13   493.8 1303.38   503.7 1306.07   513.6  1310.7
#Mann= 3 , 0 , 0
       0     .06       0   399.6    .045       0   409.6     .06       0
Bank Sta=399.6,409.6
XS Rating Curve= 0 ,0
Exp/Cntr=0.3,0.1

Type RM Length L Ch R = 1 ,286.2   ,173.8,174.8,175.8
XS GIS Cut Line= 4
     1793756.245      167011.359     1793499.301      166954.431
     1793267.161      167043.466     1793163.889       167206.76
#Sta/Elev= 30
     9.7 1394.38    48.7 1370.27    58.5 1363.43    87.7 1340.71     117 1319.68
   126.7 1313.37   136.5 1309.25     156 1305.93   165.7 1302.17   204.7  1279.8
   214.4 1275.93   224.2 1274.16   233.9 1273.53   322.8 1270.16   382.5 1266.95
   422.3 1264.02   457.1 1260.81   462.1 1260.57   467.1 1260.89     472  1261.2
   491.9 1263.88   511.8 1265.87   589.1 1272.45   598.7 1274.52   608.4 1277.99
   666.4 1305.09     676 1309.08   685.7 1311.54   695.4 1312.76     705 1315.66
#Mann= 3 , 0 , 0
       0     .06       0   457.1    .045       0   467.1     .06       0
Bank Sta=457.1,467.1
XS Rating Curve= 0 ,0
Exp/Cntr=0.3,0.1

Type RM Length L Ch R = 1 ,111.4   ,113,111.4,109.8
XS GIS Cut Line= 3
     1793600.676      166894.216     1793366.589      166827.191
     1793161.895      166895.014
#Sta/Elev= 30
     9.7 1272.34    19.5 1271.38    48.7 1269.79   136.4 1266.09   146.1 1265.88
   155.8 1265.83   185.1 1265.84   204.5 1265.71   214.3 1265.78     224 1265.29
   233.8 1263.96   243.5 1261.63   253.3 1260.52   263.1 1259.82   292.5 1259.27
   312.1 1258.57   341.5 1258.02   351.3 1257.23   370.9 1254.35   375.7 1254.16
   380.7 1253.97   385.7 1254.57   390.5 1255.15   400.3 1257.25   410.1 1258.89
   419.9 1259.69   429.7 1260.26   439.5 1260.68   449.3 1260.71   459.1 1260.51
#Mann= 3 , 0 , 0
       0     .06       0   375.7    .045       0   385.7     .06       0
Bank Sta=375.7,385.7
XS Rating Curve= 0 ,0
Exp/Cntr=0.3,0.1

Chan Stop Cuts=-1
Use User Specified Reach Order=0